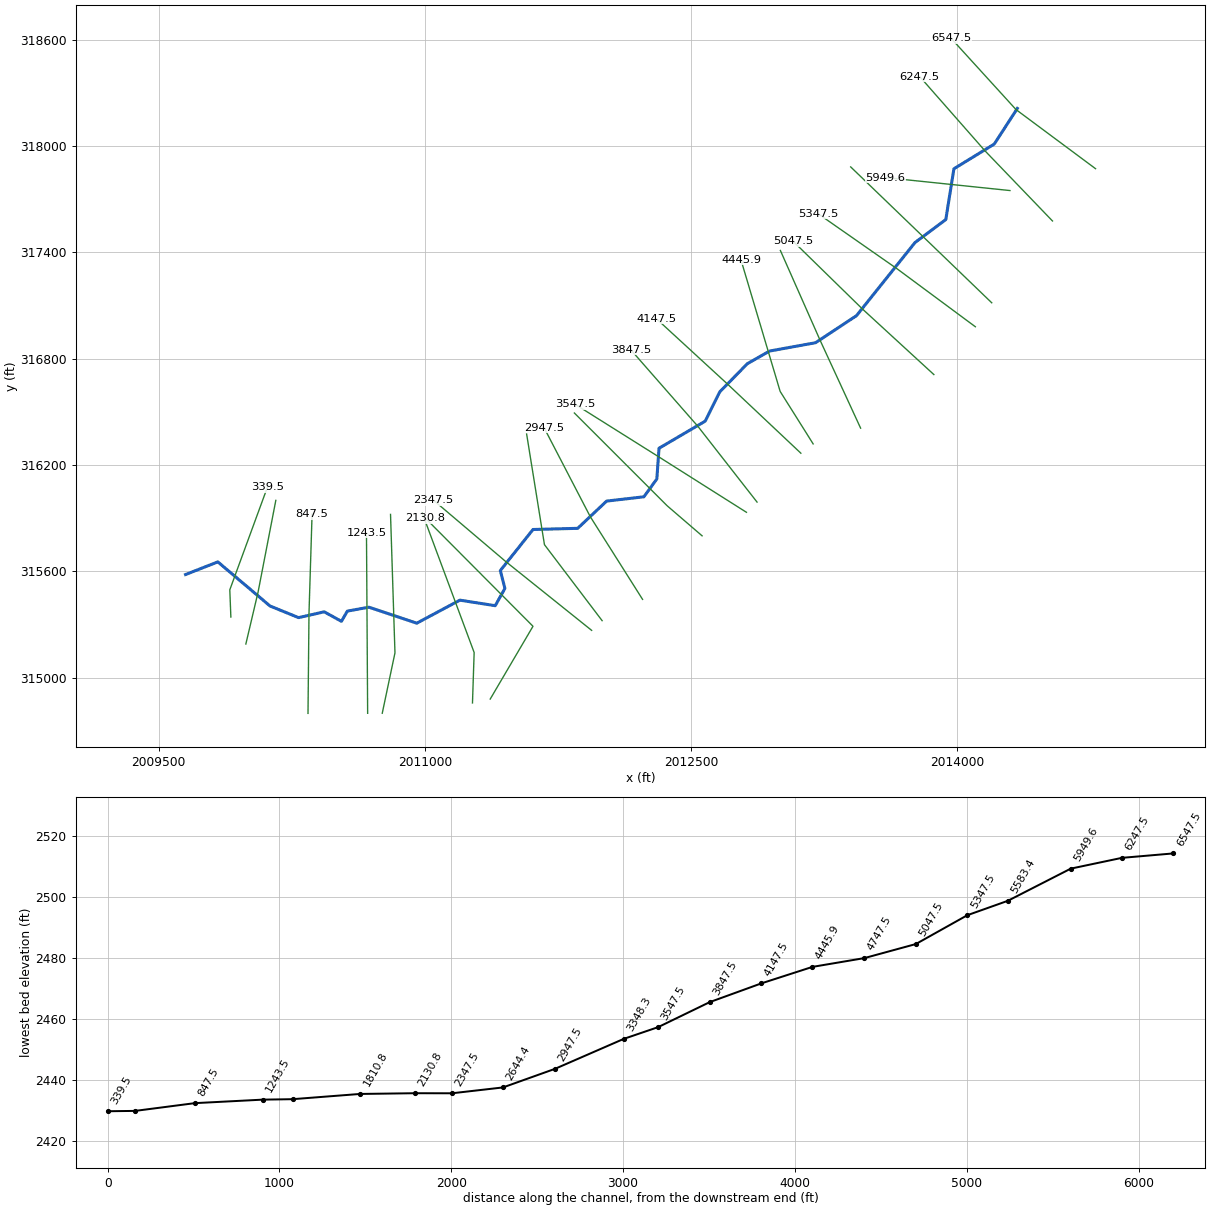
--- LaurelBrch.prj (project) ---

Proj Title=LaurelBrch
Current Plan=p01
Default Exp/Contr=0,0
English Units
Geom File=g01
Flow File=f01
Plan File=p01
BEGIN DESCRIPTION:
END DESCRIPTION:
DSS Export Rating Curves= 0
DSS Export Rating Curve Sorted= 0
DSS Export Volume Flow Curves= 0
DXF OffsetX= 0
DXF OffsetY= 0
DXF ScaleX= 0
DXF ScaleY= 0

--- LaurelBrch.p01 (plan) ---

Plan Title=Floodplain
Program Version=4.00
Geom File=g01
Flow File=f01
K Sum by GR=0
Std Step Tol=0.01
Critical Tol=0.01
Num of Std Step Trials=20
Max Error Tol=0.3
Flow Tol Ratio=0.001
Split Flow NTrial=30
Split Flow Tol=0.02
Split Flow Ratio=0.02
Log Output Level=0
Friction Slope Method=1
Unsteady Friction Slope Method=2
Unsteady Bridges Friction Slope Method=1
Global Log Level=0
CheckData=False
Run HTab=0
Run UNet=0
Run PostProcess=0
UNET Theta=0
UNET Theta Warmup=0
UNET ZTol=0
UNET ZSATol=0
UNET MxIter=0
UNET MaxInSteps=0
UNET DtIC=0
UNET DtMin=0
UNET MaxCRTS=0
UNET WFStab=0
UNET SFStab=0
UNET WFX=0
UNET SFX=0
UNET DSS MLevel=0
UNET DZMax Abort=0
UNET Convert EG Bridges=0
UNET Use Existing IB Tables=0
UNET Froude Limit=0
UNET Froude Power=0
Write IC File=0
Echo Input=False
Echo Output=False
Write Detailed=0

--- LaurelBrch.f01 (steady flow) ---

Flow Title=NFF Regression Equation
Program Version=4.00
Number of Profiles=1
Profile Names=P100yr
River Rch & RM=LaurelBrch,Main      ,6547.5
519.5050
River Rch & RM=LaurelBrch,Main      ,5583.4
545.9086
River Rch & RM=LaurelBrch,Main      ,4747.5
605.6568
River Rch & RM=LaurelBrch,Main      ,339.5
670.1164
Boundary for River Rch & Prof#=LaurelBrch,Main      ,1
Up Type=0
Dn Type=3
Dn Slope=0.003632

--- LaurelBrch.g01 (geometry) ---

Geom Title=USGS 3m DEM
Program Version=4.10

River Reach=LaurelBrch      ,Main
Reach XY= 30
     2014338.815      318213.402     2014208.607      318012.013
      2013981.44      317872.652     2013935.624      317585.839
     2013762.426      317456.457     2013432.565      317043.263
     2013201.662      316890.485     2012942.982       316843.61
     2012817.982       316772.43     2012661.732      316612.707
     2012580.135      316447.777     2012319.946      316294.763
     2012307.565      316121.388     2012234.649      316020.693
     2012024.579      315996.388     2011861.747      315842.668
      2011609.85      315836.073     2011425.621      315604.027
     2011451.662       315503.58      2011397.05      315405.924
     2011197.848      315437.153     2010955.135      315307.152
     2010685.203      315397.436     2010563.958      315375.284
     2010530.689      315317.575     2010433.467      315371.395
     2010289.369      315338.408     2010128.128      315404.222
     2009834.258      315653.164     2009652.166      315581.765

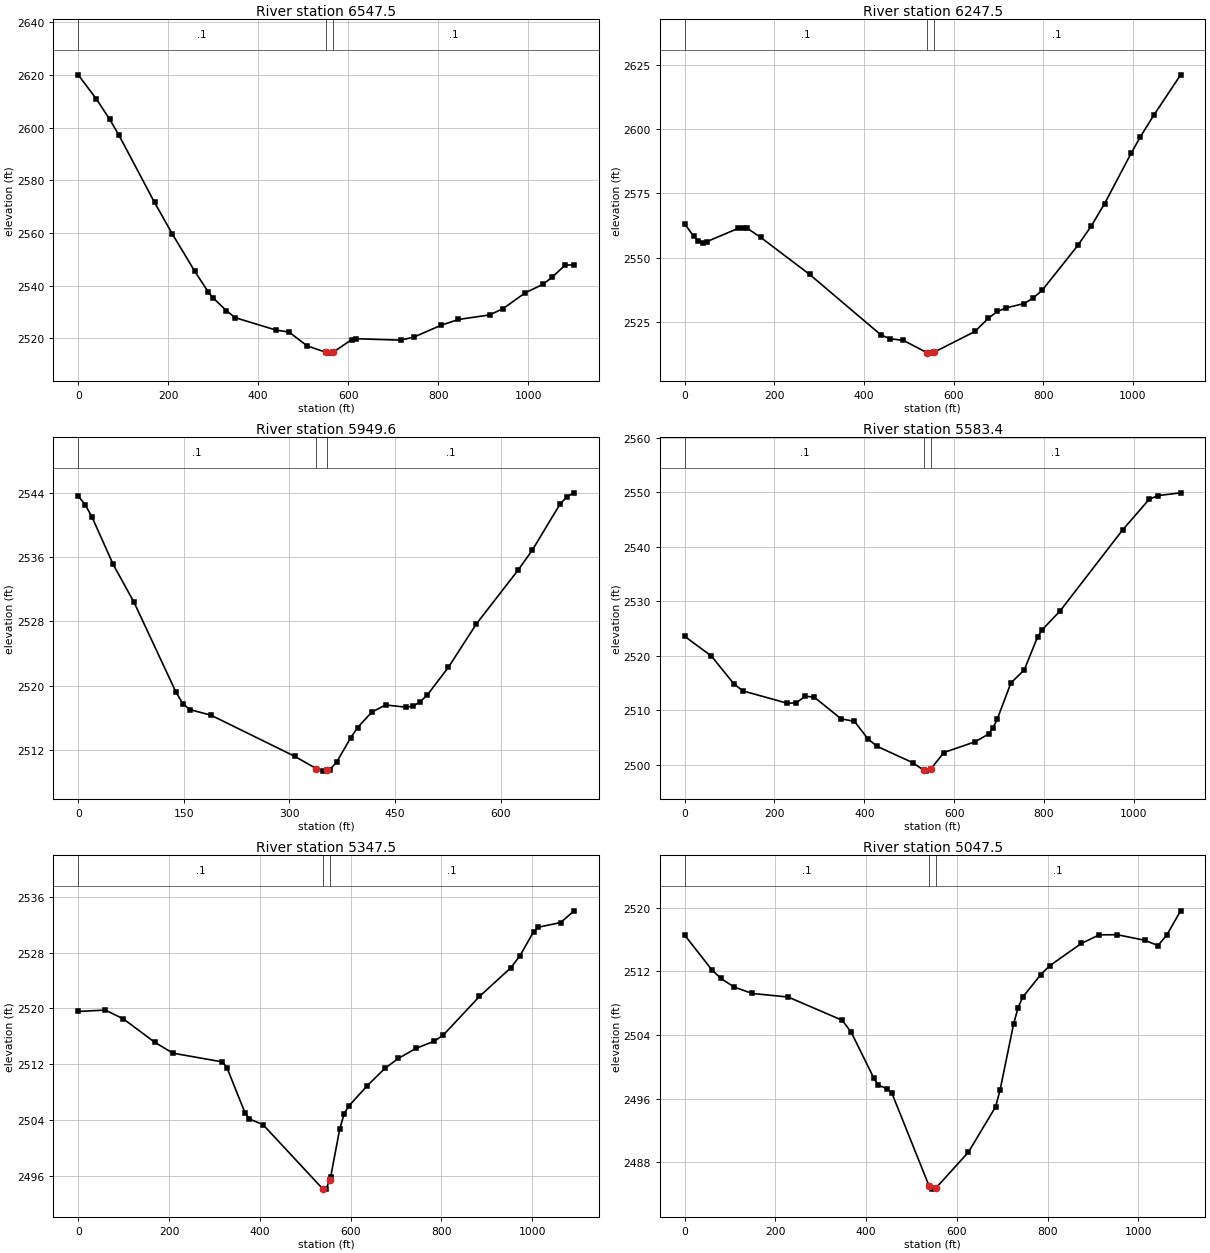
Type RM Length L Ch R = 1 ,6547.5  ,303.7,300,299.6
XS GIS Cut Line= 3
     2014779.371      317873.078     2014331.416      318206.675
     2013965.623      318609.046
#Sta/Elev= 30
       0  2620.1    39.9 2611.03    69.8 2603.25    89.8  2597.4   169.6 2571.64
   209.4 2559.59   259.3 2545.41   289.2  2537.6   299.2 2535.47   329.1 2530.54
   349.1 2527.85   438.8 2523.18   468.8 2522.37   508.7 2517.15     551 2514.69
   558.5 2514.39     566 2514.64     608 2519.54   617.8 2519.86   716.7 2519.32
   746.4 2520.51   805.7 2524.92   845.2 2527.18   914.5  2528.9   944.1 2531.28
   993.6  2537.3  1033.1 2540.55  1052.9 2543.15  1082.5 2547.85  1102.3 2547.89
#Mann= 3 , 0 , 0
       0      .1       0     551    .045       0     566      .1       0
Bank Sta=551,566
XS Rating Curve= 0 ,0
Exp/Cntr=0.3,0.1

Type RM Length L Ch R = 1 ,6247.5  ,281.8,297.9,314.9
XS GIS Cut Line= 3
       2014536.7      317577.915     2014157.088      317973.305
     2013788.709      318393.213
#Sta/Elev= 30
       0 2563.19    19.9 2558.36    29.9 2556.56    39.9 2555.89    49.8 2556.29
   119.6 2561.42   129.6 2561.72   139.5 2561.45   169.4 2557.94     279 2543.49
   438.5 2519.93   458.4 2518.53   488.3 2517.87   540.6  2513.1   548.1 2512.93
   555.6 2513.21   647.9 2521.35   677.8 2526.53   697.8 2529.12   717.7 2530.52
   757.6 2532.21   777.6 2534.32   797.5 2537.28   877.3 2554.78   907.2  2562.3
   937.1 2571.05     997 2590.82  1016.9 2597.02  1046.9 2605.41  1106.7 2621.08
#Mann= 3 , 0 , 0
       0      .1       0   540.6    .045       0   555.6      .1       0
Bank Sta=540.6,555.6
XS Rating Curve= 0 ,0
Exp/Cntr=0.3,0.1

Type RM Length L Ch R = 1 ,5949.6  ,380.9,365.8,350.7
XS GIS Cut Line= 2
      2014297.06      317749.672     2013596.574      317822.639
#Sta/Elev= 30
       0 2543.61     9.9 2542.52    19.8 2540.95    49.6  2535.1    79.4 2530.36
   138.9 2519.19   148.8 2517.75   158.7 2517.03   188.5 2516.34   307.5 2511.22
     338  2509.7   347.2 2509.38     353 2509.47   357.1 2509.54     367  2510.5
   386.9 2513.52   396.8  2514.8   416.6  2516.7   436.4 2517.61   466.2 2517.33
   476.1 2517.49     486 2518.03     496 2518.88   525.7 2522.29   565.4 2527.69
   624.9 2534.41   644.8 2536.86   684.4 2542.62   694.4 2543.54   704.3    2544
#Mann= 3 , 0 , 0
       0      .1       0     338    .045       0     353      .1       0
Bank Sta=338,353
XS Rating Curve= 0 ,0
Exp/Cntr=0.3,0.1

Type RM Length L Ch R = 1 ,5583.4  ,233,236,239.5
XS GIS Cut Line= 2
     2014194.384       317116.08     2013399.748      317883.135
#Sta/Elev= 30
       0 2523.54    59.7 2519.91   109.4 2514.84   129.4 2513.54   228.8 2511.26
   248.8 2511.35   268.6 2512.57   288.6 2512.38   348.2 2508.41   378.1 2507.95
     408 2504.75   427.8  2503.4   507.4 2500.38   533.2 2498.95   537.3 2498.82
   548.2 2499.21   577.1 2502.23   646.8  2504.2   676.6 2505.61   686.6 2506.75
   696.5 2508.45   726.4 2514.98   756.2 2517.39     786 2523.45     796 2524.74
   835.8 2528.18   975.1 2543.04  1034.8 2548.71  1054.7 2549.36  1104.4 2549.86
#Mann= 3 , 0 , 0
       0      .1       0   533.2    .045       0   548.2      .1       0
Bank Sta=533.2,548.2
XS Rating Curve= 0 ,0
Exp/Cntr=0.3,0.1

Type RM Length L Ch R = 1 ,5347.5  ,302.3,299.9,296.2
XS GIS Cut Line= 3
     2014102.118      316980.752     2013663.665      317306.058
     2013215.986      317619.086
#Sta/Elev= 30
       0 2519.57    59.6 2519.77    99.3 2518.51   168.8 2515.14   208.5 2513.59
   317.6 2512.33   327.6  2511.5   367.3 2505.03   377.2 2504.14     407 2503.33
   538.5 2494.12     546 2494.08   553.5 2495.39   555.9 2495.81   575.8 2502.66
   585.7 2504.91   595.6 2505.98   635.3 2508.83   675.1 2511.39   704.9 2512.83
   744.6  2514.3   784.3 2515.31   804.2  2516.2   883.6 2521.72   953.2 2525.87
     973 2527.59  1002.8    2531  1012.8 2531.65  1062.4 2532.33  1092.2 2534.01
#Mann= 3 , 0 , 0
       0      .1       0   538.5    .045       0   553.5      .1       0
Bank Sta=538.5,553.5
XS Rating Curve= 0 ,0
Exp/Cntr=0.3,0.1

Type RM Length L Ch R = 1 ,5047.5  ,308.9,300,291.5
XS GIS Cut Line= 3
     2013868.337      316710.809     2013466.675      317080.339
     2013075.711      317463.193
#Sta/Elev= 30
       0 2516.57    59.5 2512.23    79.4 2511.14   109.2 2510.03   148.8 2509.23
   228.2 2508.78   347.3 2505.85   367.2 2504.33   416.8 2498.58   426.7 2497.68
   446.6 2497.24   456.5  2496.7   538.3 2485.05   545.8  2484.6   553.3 2484.71
   625.4 2489.26   685.1 2494.95     695 2497.05   724.9 2505.39   734.8 2507.44
   744.8 2508.75   784.6 2511.59   804.5 2512.72   874.1 2515.52   913.9 2516.61
   953.7 2516.62  1013.4 2515.93  1043.2 2515.26  1063.1 2516.64    1093 2519.63
#Mann= 3 , 0 , 0
       0      .1       0   538.3    .045       0   553.3      .1       0
Bank Sta=538.3,553.3
XS Rating Curve= 0 ,0
Exp/Cntr=0.3,0.1

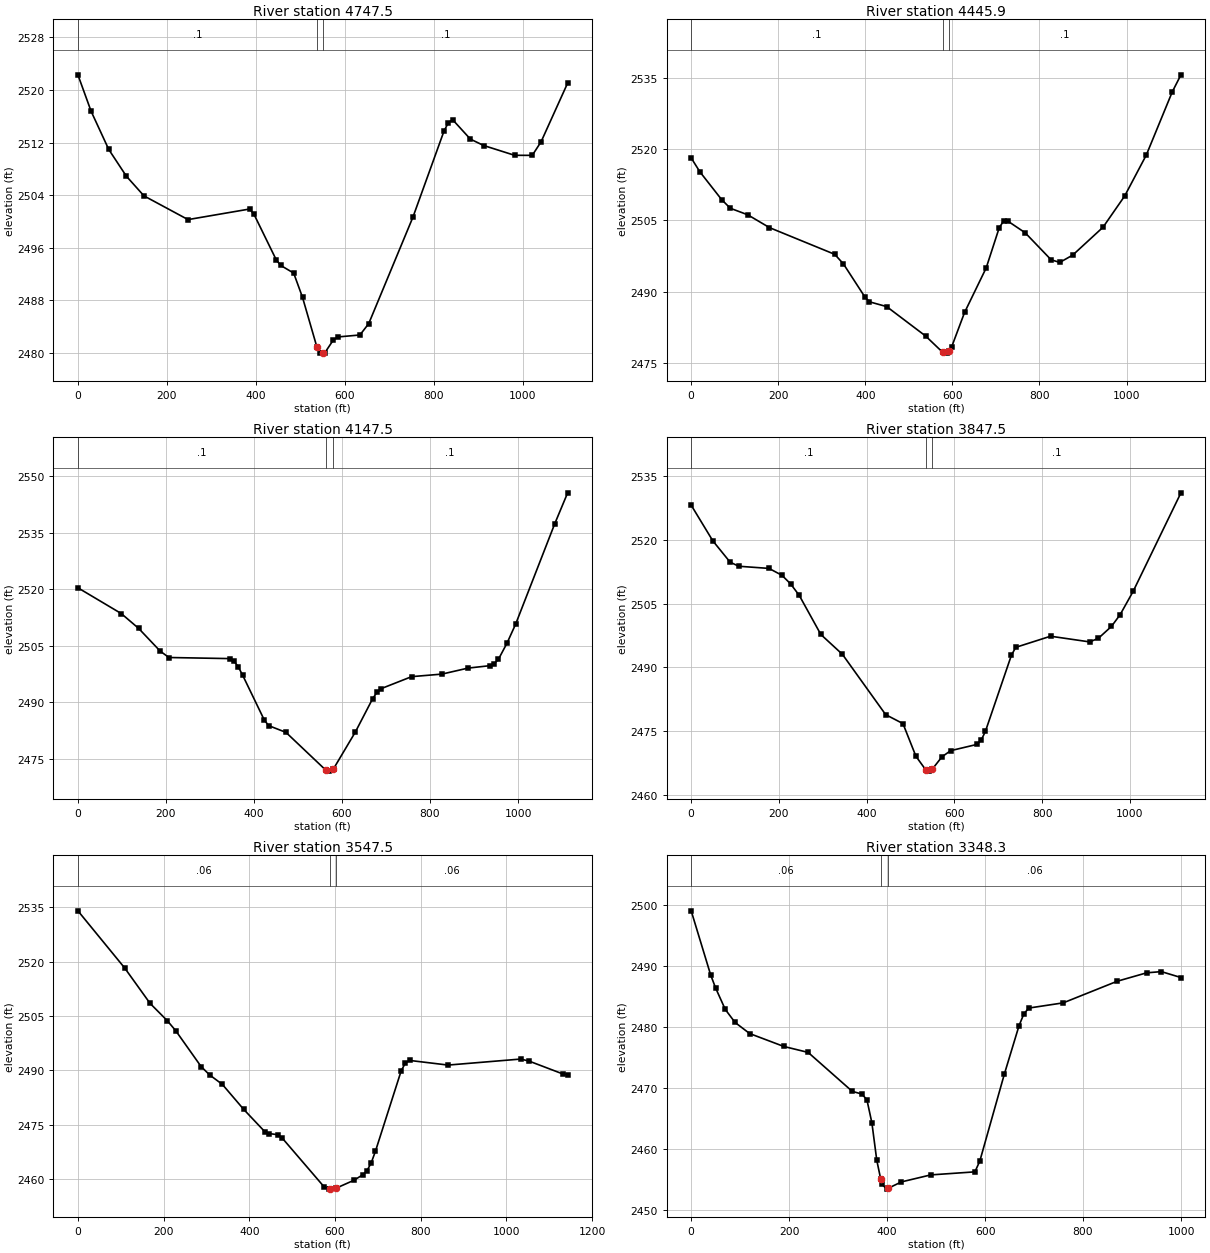
Type RM Length L Ch R = 1 ,4747.5  ,304.8,301.6,298.7
XS GIS Cut Line= 3
     2013455.651      316408.277     2013228.217      316902.701
     2013003.609      317411.377
#Sta/Elev= 30
       0 2522.31    29.7 2516.76    69.3 2510.96   108.8  2506.9   148.4  2503.9
   247.4 2500.29   385.9  2501.9   395.8 2501.07   445.3 2494.21   455.2 2493.34
   484.8 2492.15   504.6 2488.47   536.7 2480.96   544.2 2480.04   551.7    2480
   554.2 2479.98     574 2481.99   583.9 2482.44   633.6 2482.74   653.4 2484.47
   752.8 2500.68   822.2  2513.7   832.2 2515.04   842.1 2515.47   881.8 2512.53
   911.6 2511.56   981.1 2510.07  1020.8 2510.06  1040.7 2512.14  1100.3 2521.06
#Mann= 3 , 0 , 0
       0      .1       0   536.7    .045       0   551.7      .1       0
Bank Sta=536.7,551.7
XS Rating Curve= 0 ,0
Exp/Cntr=0.3,0.1

Type RM Length L Ch R = 1 ,4445.9  ,286.6,298.4,310.6
XS GIS Cut Line= 3
     2013188.296      316319.322     2013002.412      316615.551
     2012781.548      317358.687
#Sta/Elev= 30
       0 2518.13      20 2515.21    69.9 2509.38    89.9 2507.55   129.9 2506.18
   179.9 2503.48   329.7 2497.87   349.7 2495.86   399.4 2488.85   409.4 2487.89
   449.1 2486.88   538.6 2480.69   577.5 2477.29   588.3  2477.1   592.5 2477.64
   598.2 2478.38     628 2485.65   677.7 2495.02   707.5 2503.43   717.5 2504.86
   727.4 2504.85   767.2  2502.4   826.8 2496.72   846.7 2496.17   876.5 2497.71
   946.1 2503.57   995.8 2510.13  1045.5 2518.75  1105.1 2532.02    1125  2535.6
#Mann= 3 , 0 , 0
       0      .1       0   577.5    .045       0   592.5      .1       0
Bank Sta=577.5,592.5
XS Rating Curve= 0 ,0
Exp/Cntr=0.3,0.1

Type RM Length L Ch R = 1 ,4147.5  ,303.3,299.9,297.5
XS GIS Cut Line= 3
     2013118.998      316266.855     2012703.729       316658.95
     2012305.383      317025.847
#Sta/Elev= 30
       0 2520.39    98.5 2513.54   137.9 2509.61   187.1 2503.54   206.8 2501.86
   344.6 2501.57   354.5 2500.91   364.3 2499.39   374.2 2497.18   423.4 2485.26
   433.3 2483.76   472.7 2481.96   563.6 2471.88   571.1 2471.66   578.6 2472.17
     581 2472.33   630.2 2482.02   669.6  2490.9   679.4  2492.6   689.3  2493.6
   758.2 2496.77   827.1 2497.45   886.2 2499.04   935.4 2499.68   945.3 2500.18
   955.2 2501.34   974.8 2505.65   994.5 2510.72  1083.2 2537.36  1112.7 2545.63
#Mann= 3 , 0 , 0
       0      .1       0   563.6    .045       0   578.6      .1       0
Bank Sta=563.6,578.6
XS Rating Curve= 0 ,0
Exp/Cntr=0.3,0.1

Type RM Length L Ch R = 1 ,3847.5  ,294.8,299.9,305.1
XS GIS Cut Line= 3
     2012872.147      315990.804     2012539.038       316418.24
     2012160.832      316850.844
#Sta/Elev= 30
       0 2528.18    49.3 2519.78    88.7 2514.76   108.4 2513.79   177.4 2513.28
   206.9 2511.66   226.6 2509.64   246.3 2506.93   295.6 2497.71   344.8 2493.03
   443.4 2478.82   482.8 2476.71   512.4    2469   534.4 2465.86   541.9 2465.51
   549.4 2465.94   571.6 2468.87   591.4 2470.33   650.9 2471.79   660.8 2472.74
   670.7 2474.86   730.1 2492.84     740 2494.68   819.3  2497.3   908.5 2495.96
   928.3 2496.81     958  2499.6   977.8 2502.36  1007.6 2507.88  1116.5 2531.09
#Mann= 3 , 0 , 0
       0      .1       0   534.4    .045       0   549.4      .1       0
Bank Sta=534.4,549.4
XS Rating Curve= 0 ,0
Exp/Cntr=0.3,0.1

Type RM Length L Ch R = 1 ,3547.5  ,201.6,199.3,195.6
XS GIS Cut Line= 3
     2012812.344      315933.204     2012309.908      316251.649
     2011846.035      316543.646
#Sta/Elev= 30
       0 2533.98   109.1 2518.24   168.5 2508.47   208.2 2503.76     228    2501
   287.5 2491.08   307.3 2488.78   337.1 2486.16   386.6 2479.32   436.2 2473.13
   446.1 2472.61     466 2472.31   475.9  2471.5     575 2457.87   584.9  2457.3
   587.4 2457.31   602.4 2457.55   644.7 2459.77   664.6 2461.24   674.6 2462.36
   684.6 2464.56   694.5 2467.77   754.3 2489.83   764.3 2492.09   774.2 2492.76
   863.9 2491.48  1033.4 2493.14  1053.3 2492.56    1133 2488.98    1143 2488.82
#Mann= 3 , 0 , 0
       0     .06       0   587.4    .045       0   602.4     .06       0
Bank Sta=587.4,602.4
XS Rating Curve= 0 ,0
Exp/Cntr=0.3,0.1

Type RM Length L Ch R = 1 ,3348.3  ,406.1,400.9,393.7
XS GIS Cut Line= 3
     2012562.523      315800.402     2012366.554      315969.269
     2011842.916      316493.763
#Sta/Elev= 30
       0 2499.06    39.8 2488.55    49.8 2486.43    69.6  2482.9    89.6 2480.77
   119.4 2478.95     189 2476.84   238.8 2475.86   328.8 2469.48   348.8 2469.03
   358.8 2468.08   368.9 2464.32   378.9 2458.18     387 2455.07   388.9 2454.34
   398.9 2453.46     402 2453.59     429 2454.64     489 2455.79   579.2 2456.29
   589.2 2458.05   639.3  2472.3   669.3 2480.24   679.3  2482.2   689.4 2483.13
   759.5 2483.98   869.6 2487.52   929.7  2488.9   959.8  2489.1   999.8 2488.13
#Mann= 3 , 0 , 0
       0     .06       0     387    .045       0     402     .06       0
Bank Sta=387,402
XS Rating Curve= 0 ,0
Exp/Cntr=0.3,0.1

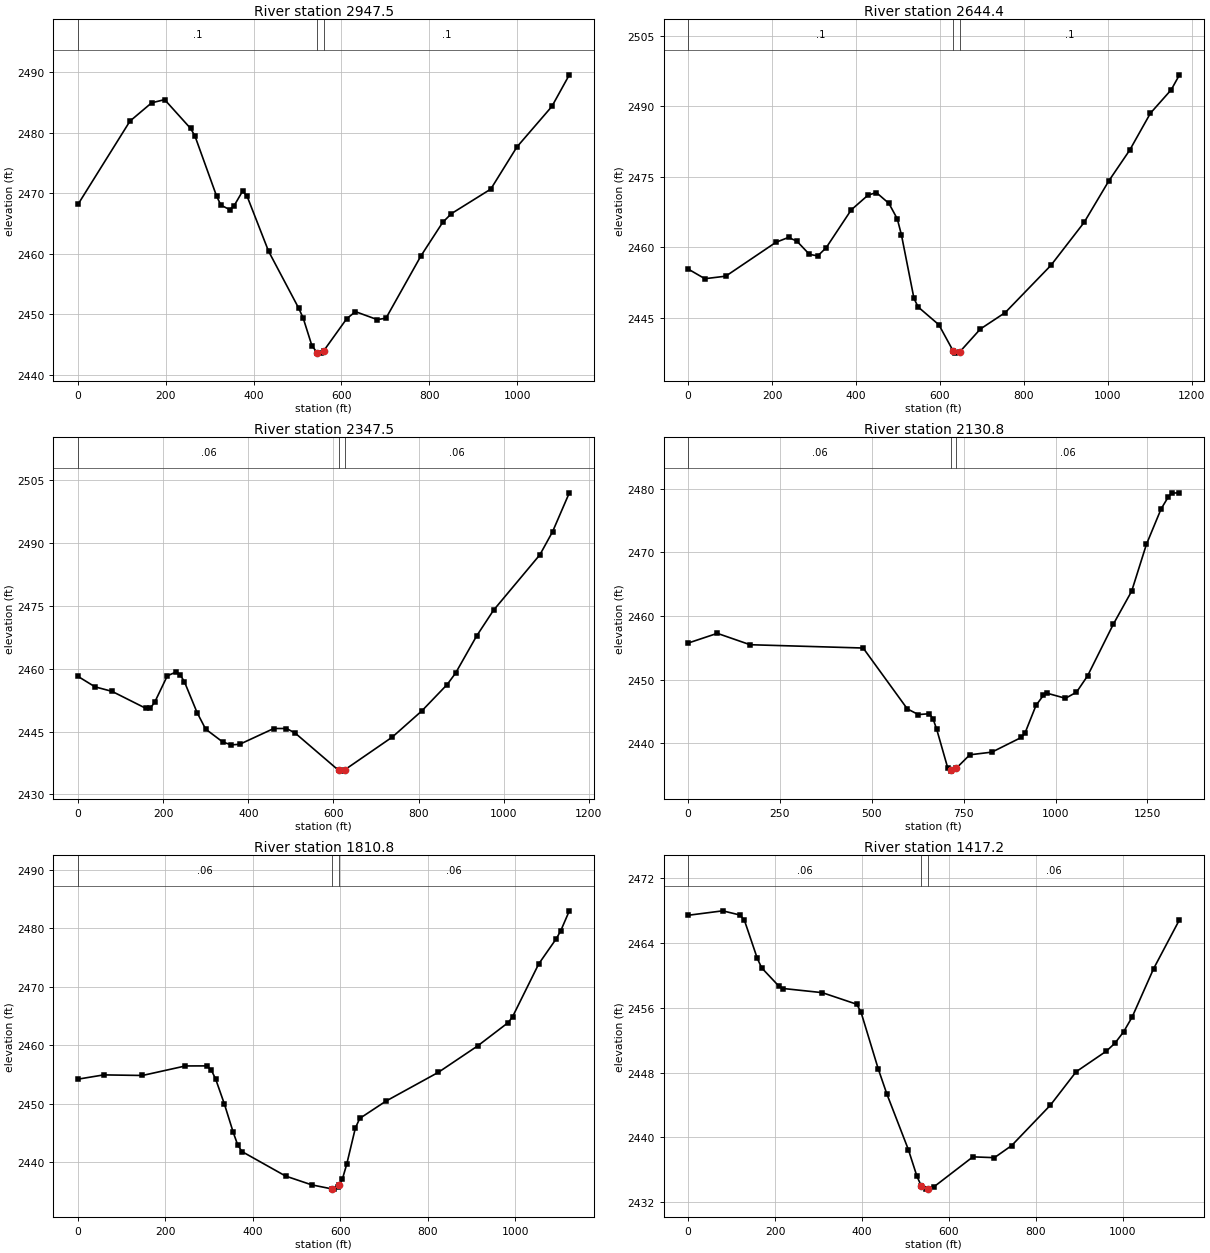
Type RM Length L Ch R = 1 ,2947.5  ,311.9,302.7,295.6
XS GIS Cut Line= 3
     2012227.238      315441.433     2011932.466      315908.569
     2011671.806      316411.732
#Sta/Elev= 30
       0 2468.19   118.4 2481.96   167.7 2484.98   197.3 2485.51   256.4 2480.75
   266.3 2479.51   315.6 2469.57   325.5 2468.06   345.2 2467.34   355.1 2467.91
   374.8 2470.37   384.7 2469.62     434 2460.45     503 2450.98   512.9 2449.39
   532.6 2444.86   544.9 2443.63   552.4  2443.6   559.9 2444.01     612 2449.29
   631.9 2450.46   681.6 2449.14   701.5 2449.38     781 2459.67   830.7 2465.23
   850.6 2466.67   940.1 2470.72   999.7 2477.69  1079.3 2484.39    1119 2489.61
#Mann= 3 , 0 , 0
       0      .1       0   544.9    .045       0   559.9      .1       0
Bank Sta=544.9,559.9
XS Rating Curve= 0 ,0
Exp/Cntr=0.3,0.1

Type RM Length L Ch R = 1 ,2644.4  ,280.4,296.8,312.6
XS GIS Cut Line= 3
     2011999.344      315321.275     2011674.407      315750.368
     2011573.982      316375.048
#Sta/Elev= 30
       0 2455.38    39.9 2453.32    89.7 2453.86   209.3 2461.07   239.2  2462.1
   259.2 2461.31   289.1 2458.49     309 2458.18   328.9  2459.9   388.7 2467.96
   428.6 2471.09   448.5 2471.65   478.4 2469.35   498.4 2466.06   508.3 2462.66
   538.2 2449.13   548.1 2447.31   597.6 2443.52   631.9  2437.9   637.1 2437.49
   646.9 2437.71   696.4 2442.62   755.7 2446.12   864.5 2456.16   943.6 2465.29
  1002.9 2474.18  1052.3 2480.67  1101.7 2488.53  1151.2 2493.51  1170.9 2496.69
#Mann= 3 , 0 , 0
       0      .1       0   631.9    .045       0   646.9      .1       0
Bank Sta=631.9,646.9
XS Rating Curve= 0 ,0
Exp/Cntr=0.3,0.1

Type RM Length L Ch R = 1 ,2347.5  ,218.8,216.3,214.5
XS GIS Cut Line= 3
     2011940.205      315266.621     2011456.993      315654.545
     2011049.942      316000.788
#Sta/Elev= 30
       0  2458.2      40  2455.7      80 2454.62   159.9 2450.54   169.9 2450.64
   179.9 2451.97   209.9 2458.34   229.9 2459.22   239.9 2458.59   249.9 2456.93
   279.8 2449.54   299.8 2445.61   339.8 2442.54   359.8 2441.84   379.8 2441.98
   459.8 2445.75   489.7 2445.75   509.7 2444.69   612.2 2435.75   619.7 2435.57
   627.2 2435.93   738.4 2443.72   807.7 2449.97   867.1 2456.26   886.9 2458.99
   936.3 2467.86   975.9 2473.99  1084.8 2487.24  1114.5 2492.73    1154 2502.04
#Mann= 3 , 0 , 0
       0     .06       0   612.2    .045       0   627.2     .06       0
Bank Sta=612.2,627.2
XS Rating Curve= 0 ,0
Exp/Cntr=0.3,0.1

Type RM Length L Ch R = 1 ,2130.8  ,330,318.6,308.5
XS GIS Cut Line= 3
     2011368.829       314878.68     2011609.779      315289.631
     2011003.108      315900.472
#Sta/Elev= 30
       0 2455.74    79.4 2457.27   168.7 2455.48   476.4 2454.96   596.5 2445.39
   626.5 2444.49   656.6 2444.62   666.6 2443.82   676.6 2442.16   706.6 2436.09
   714.2 2435.71   716.6 2435.59   729.2 2436.01   766.7 2438.16   826.8 2438.58
   906.8 2440.89   916.8 2441.57   946.9 2445.94   966.9 2447.51   976.9 2447.85
    1027 2447.05    1057 2448.01    1087 2450.56  1157.1 2458.69  1207.2 2463.91
  1247.2 2471.25  1287.2 2476.84  1307.3 2478.78  1317.3 2479.34  1337.3 2479.38
#Mann= 3 , 0 , 0
       0     .06       0   714.2    .045       0   729.2     .06       0
Bank Sta=714.2,729.2
XS Rating Curve= 0 ,0
Exp/Cntr=0.3,0.1

Type RM Length L Ch R = 1 ,1810.8  ,400.4,393,385.6
XS GIS Cut Line= 3
     2011268.872      314856.857     2011278.299      315141.612
      2010986.43      315927.574
#Sta/Elev= 30
       0 2454.18      59 2454.91   147.4 2454.81   245.6 2456.44   294.9 2456.45
   304.9 2455.72   314.8 2454.18   334.8  2449.9   354.8  2445.1   364.8 2442.99
   374.7 2441.79   474.6 2437.59   534.4 2436.08   581.7 2435.37   584.3 2435.35
   594.3 2435.68   596.7    2436   604.3 2437.03   614.3 2439.59   634.2 2445.83
   644.2 2447.46   704.1 2450.42   823.9 2455.35   913.7 2459.87   983.6 2463.87
   993.6 2464.88  1053.4 2473.92  1093.4 2478.22  1103.4 2479.54  1123.3    2483
#Mann= 3 , 0 , 0
       0     .06       0   581.7    .045       0   596.7     .06       0
Bank Sta=581.7,596.7
XS Rating Curve= 0 ,0
Exp/Cntr=0.3,0.1

Type RM Length L Ch R = 1 ,1417.2  ,174.4,173.7,172.9
XS GIS Cut Line= 3
     2010760.509      314798.616     2010832.156      315139.527
     2010807.139      315921.319
#Sta/Elev= 30
       0  2467.4    79.6 2467.95   119.4 2467.43   129.4  2466.8   159.2 2462.08
   169.2 2460.92     209 2458.65     219 2458.37   308.6 2457.86     388 2456.43
   397.9 2455.44   437.5 2448.45   457.3 2445.36   506.8  2438.5   526.6  2435.2
   536.8 2433.99   546.4 2433.63   551.8 2433.67   566.2 2433.94   655.3 2437.61
   704.8 2437.51   744.4    2439   833.5 2443.98   892.9 2448.11   962.2 2450.64
     982 2451.62  1001.8 2453.01  1021.6 2454.84  1071.1 2460.82  1130.6 2466.85
#Mann= 3 , 0 , 0
       0     .06       0   536.8    .045       0   551.8     .06       0
Bank Sta=536.8,551.8
XS Rating Curve= 0 ,0
Exp/Cntr=0.3,0.1

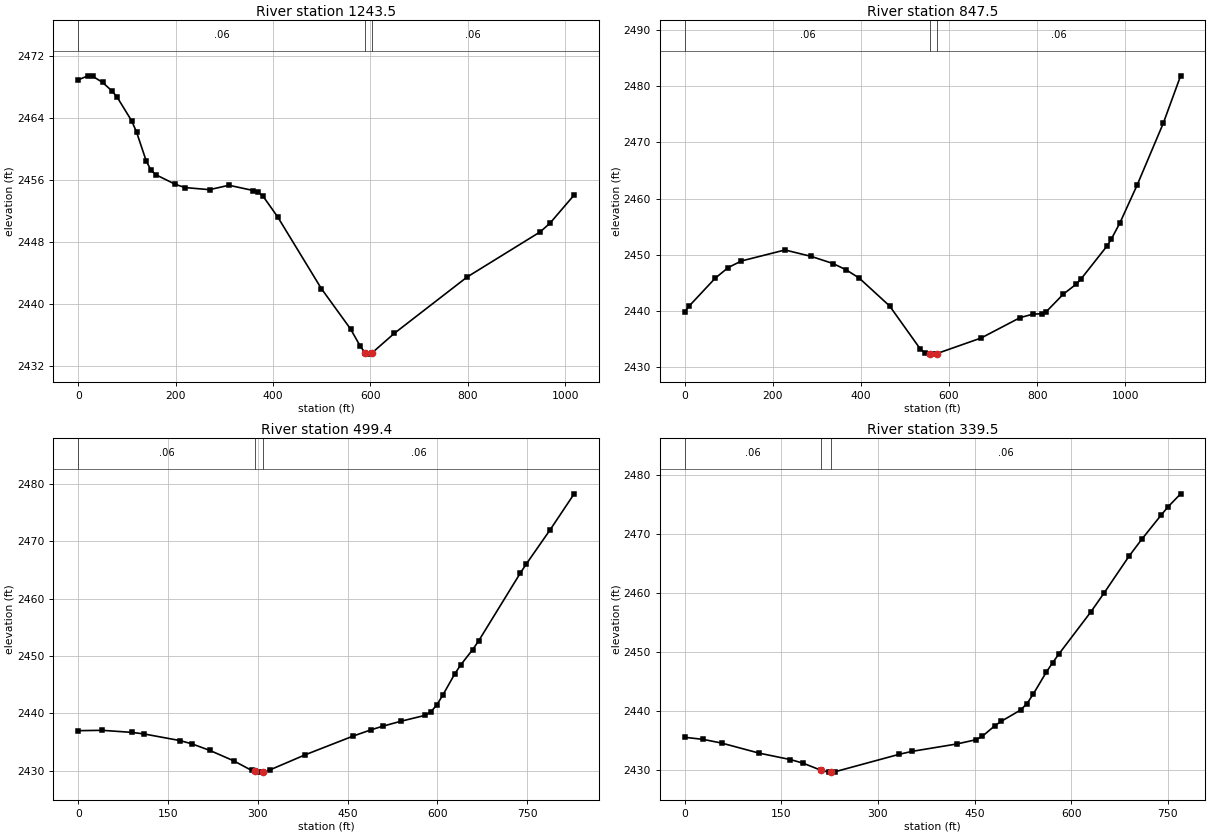
Type RM Length L Ch R = 1 ,1243.5  ,394.2,394.7,392.3
XS GIS Cut Line= 2
     2010678.229      314798.364     2010671.628       315817.08
#Sta/Elev= 30
       0 2468.92      20 2469.44      30 2469.37    49.9  2468.6    69.9 2467.45
    79.9 2466.69   109.9 2463.61   119.8 2462.18   139.8 2458.42   149.8 2457.21
   159.8 2456.65   199.8 2455.41   219.7    2455   269.7 2454.73   309.6  2455.3
   359.6 2454.62   369.5 2454.41   379.5  2453.9   409.5 2451.23   499.4 2441.95
   559.3 2436.74   579.3 2434.52   589.3 2433.64   599.3 2433.48   604.3 2433.68
   649.2 2436.16     799 2443.45   948.8 2449.27   968.8 2450.38  1018.7 2454.04
#Mann= 3 , 0 , 0
       0     .06       0   589.3    .045       0   604.3     .06       0
Bank Sta=589.3,604.3
XS Rating Curve= 0 ,0
Exp/Cntr=0.3,0.1

Type RM Length L Ch R = 1 ,847.5   ,352.5,347.9,344
XS GIS Cut Line= 3
     2010342.199      314797.929     2010347.752      315362.238
     2010365.165      315923.404
#Sta/Elev= 30
       0 2439.84     9.9 2440.86    69.3 2445.84      99 2447.74   128.7  2448.9
   227.7 2450.86   287.1 2449.72   336.6 2448.45   366.3 2447.34     396 2445.87
   465.3 2440.89   534.6 2433.27   544.5 2432.61   556.8 2432.35   564.3 2432.33
   571.8 2432.41   672.7 2435.19   761.3 2438.82   790.9 2439.45   810.6 2439.51
   820.4 2439.85   859.8 2443.02   889.4 2444.81   899.2 2445.65   958.3 2451.52
   968.2 2452.75   987.9 2455.66  1027.3 2462.44  1086.4  2473.4  1125.8 2481.84
#Mann= 3 , 0 , 0
       0     .06       0   556.8    .045       0   571.8     .06       0
Bank Sta=556.8,571.8
XS Rating Curve= 0 ,0
Exp/Cntr=0.3,0.1

Type RM Length L Ch R = 1 ,499.4   ,162.4,159.9,156.6
XS GIS Cut Line= 3
      2009991.99      315189.562     2010060.602      315481.246
     2010160.857      316000.541
#Sta/Elev= 30
       0    2437      40 2437.06    89.9  2436.7   109.9 2436.43   169.8 2435.28
   189.8 2434.71   219.7 2433.57   259.7 2431.75   289.7 2430.08   294.5 2429.93
   299.6 2429.78   309.5 2429.81   319.6 2430.14   379.5 2432.81   459.3 2436.06
   489.2 2437.15   509.2 2437.79   539.1 2438.64   579.1 2439.66     589 2440.27
     599 2441.47     609 2443.18     629 2446.88   638.9 2448.44   658.9 2451.11
   668.9 2452.63   738.7 2464.47   748.7 2466.05   788.6 2472.02   828.5 2478.25
#Mann= 3 , 0 , 0
       0     .06       0   294.5    .045       0   309.5     .06       0
Bank Sta=294.5,309.5
XS Rating Curve= 0 ,0
Exp/Cntr=0.3,0.1

Type RM Length L Ch R = 1 ,339.5   ,311.3,338.9,366.5
XS GIS Cut Line= 3
     2009907.557      315341.748     2009901.641      315495.566
      2010113.14      316073.859
#Sta/Elev= 30
       0 2435.57    28.9 2435.21    57.7 2434.58   115.4 2432.89   163.9  2431.8
   183.7 2431.19   211.9 2429.97   223.4 2429.67   226.9 2429.69   233.4 2429.74
   332.7 2432.68   352.6 2433.18   422.1 2434.43   451.9 2435.15   461.8 2435.73
   481.7 2437.55   491.6 2438.29   521.4 2440.19   531.3 2441.28   541.3 2442.94
   561.1 2446.57   571.1  2448.2     581  2449.7   630.6 2456.83   650.5 2459.93
   690.2 2466.32   710.1 2469.19   739.9 2473.25   749.8 2474.54   769.7 2476.79
#Mann= 3 , 0 , 0
       0     .06       0   211.9    .045       0   226.9     .06       0
Bank Sta=211.9,226.9
XS Rating Curve= 0 ,0
Exp/Cntr=0.3,0.1

Chan Stop Cuts=-1
Use User Specified Reach Order=0
Composite Channel Slope=5